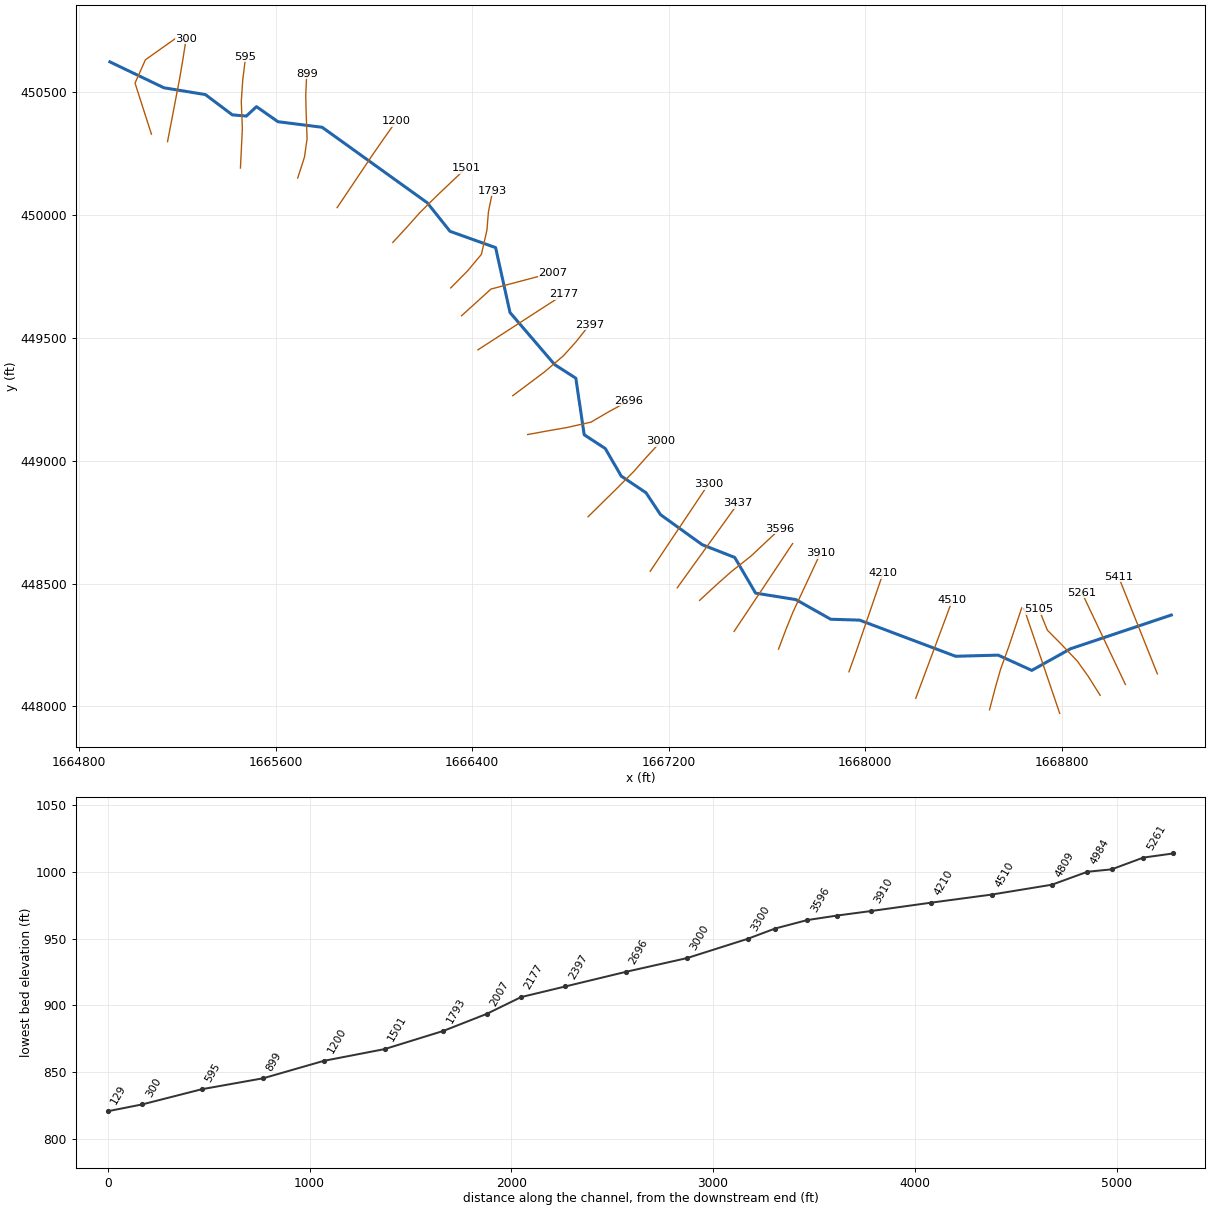
--- HckmanRn.prj (project) ---

Proj Title=HckmanRn
Current Plan=p01
Default Exp/Contr=0,0
English Units
Geom File=g01
Flow File=f01
Plan File=p01
BEGIN DESCRIPTION:
---------- MODELED AS PART OF WVEM CTP PROGRAM, 2025----------
Stream Name: Hickman Run
Flood Zone: AFH
Marshall County, WV
HEC-RAS Version: RAS 6.6
Vertical Datum: NAVD88
Projection: NAD 1983 StatePlane West Virginia N FIPS 4701 (US Feet)
Terrain: 1-meter West Virginia FEMA R3 South Central (collected 2018-2019)
Land Use: 2024 NLCD
Hydrologic Method:
Duda et al., "Estimation of magnitude and frequency of floods for rural, unregulated streams in and near Virginia and West Virginia." September 8, 2025.
Additional Model Notes:
None
END DESCRIPTION:
DSS Export Rating Curves= 0
DSS Export Rating Curve Sorted= 0
DSS Export Volume Flow Curves= 0
DXF OffsetX= 0
DXF OffsetY= 0
DXF ScaleX= 0
DXF ScaleY= 0

--- HckmanRn.p01 (plan) ---

Plan Title=Floodplain
Program Version=6.60
Short Identifier=Floodplain
Geom File=g01
Flow File=f01
Subcritical Flow
K Sum by GR= 0
Std Step Tol= 0.01
Critical Tol= 0.01
Num of Std Step Trials= 20
Max Error Tol= 0.3
Flow Tol Ratio= 0.001
Split Flow NTrial= 30
Split Flow Tol= 0.02
Split Flow Ratio= 0.02
Log Output Level= 0
Friction Slope Method= 1
Unsteady Friction Slope Method= 2
Unsteady Bridges Friction Slope Method= 1
Parabolic Critical Depth
Global Vel Dist= 0 , 0 , 0
Global Log Level= 0
CheckData=False
Encroach Param=-1 ,0,0, 0
Flow Ratio Tolerance=0.1
Flow Ratio Min Ratio=0.5
Flow Ratio Max Ratio=4
Flow Ratio Max Iterations= 10
Mapping Interval=1HOUR
Computation Time Step Use Courant=        0
Computation Time Step Use Time Series=    0
Computation Time Step Count To Double=0
Computation Time Step Max Doubling=0
Computation Time Step Max Halving=0
Computation Time Step Residence Courant=0
Run HTab= 0
Run UNet= 0
Run Sediment= 0
Run PostProcess= 0
Run WQNet= 0
Run RASMapper=-1
UNET Theta= 0
UNET Theta Warmup= 0
UNET ZTol= 0
UNET ZSATol= 0
UNET MxIter= 0
UNET Max Iter WO Improvement= 0
UNET MaxInSteps= 0
UNET DtIC= 0
UNET DtMin= 0
UNET MaxCRTS= 0
UNET WFStab= 0
UNET SFStab= 0
UNET WFX= 1
UNET SFX= 1
UNET Gravity=32.17405
UNET 1D Methodology=Finite Difference
UNET DSS MLevel= 1
UNET Pardiso=0
UNET DZMax Abort= 0
UNET Use Existing IB Tables= 0
UNET Froude Reduction=False
UNET Froude Limit= 0
UNET Froude Power= 0
UNET D1 Cores= 0
UNET WindReference=Eulerian
UNET WindDragFormulation=Hsu (1988)
UNET D2 Coriolis=0
UNET D2 Cores= 0
UNET D2 Theta= 1
UNET D2 Theta Warmup= 1
UNET D2 Z Tol= 0.01
UNET D2 Volume Tol= 0.01
UNET D2 Max Iterations= 20
UNET D2 Advanced Convergence=0
UNET D2 WS Max Tol=0.15
UNET D2 WS RMS Tol=0.002
UNET D2 WS Stall Tol=1
UNET D2 Equation= 0
UNET D2 RampUpFraction=0.1
UNET D2 TimeSlices= 1
UNET D2 Turbulence Formulation=Non-Conservative (original)
UNET D2 Eddy Viscosity=0.3
UNET D2 Transverse Eddy Viscosity=0.1
UNET D2 Smagorinsky Mixing=0
UNET D2 BCVolumeCheck=0
UNET D2 Cores=0
UNET D2 SolverType=PARDISO (Direct)
UNET D2 Minimum Iterations= 3
UNET D2 Maximum Iterations= 30
UNET D2 Restart Number= 10
UNET D2 Relaxation Coeff=1.3
UNET D2 SOR Precondition Iterations= 10
UNET D2 ILUT Maximum Fill= 8
UNET D2 ILUT Tolerance=1E-08
UNET D2 Convergence Tolerance=0.00001
PS Theta= 1
PS WS Tol= 0.01
PS Volume Tol= 0.01
PS Max Iterations= 20
PS Equation= 0
PS Advance Time Step=-1
PS Target Courant=0.9
PS Time Slices= 1
PS Iterate With 2D=0
PS Project Initial WSE from DS=-1
PS Ramp Up Initial WSE from US=-1
PS Cores=0
UNET D1D2 MaxIter= 0
UNET D1D2 ZTol=0.01
UNET D1D2 QTol=0.1
UNET D1D2 MinQTol=1
Write IC File= 0
Write IC File at Fixed DateTime=0
Write IC File at Sim End=0
Echo Input=False
Echo Parameters=False
Echo Output=False
Write Detailed= 0
HDF Write Warmup=0
HDF Write Time Slices=0
HDF Flush=0
HDF Compression= 1
HDF Chunk Size= 1
HDF Spatial Parts= 1
HDF Use Max Rows=0
HDF Fixed Rows= 1
Calibration Method= 0
Calibration Iterations= 20
Calibration Max Change=0.05
Calibration Tolerance=0.2
Calibration Maximum=1.5
Calibration Minimum=0.5
Calibration Optimization Method= 1
WQ AD Non Conservative
WQ ULTIMATE=-1
WQ Max Comp Step=1HOUR
WQ Output Interval=15MIN
WQ Output Selected Increments= 0
WQ Create Restart=0
WQ Fixed Restart=0
WQ System Summary=0
WQ Write To DSS=0
Sorting and Armoring Iterations= 10
XS Update Threshold= 0.02
Bed Roughness Predictor= 0
Processes Affected by Predictor=Sediment Only
Hydraulics Update Threshold= 0.02
Energy Slope Method= 1
Volume Change Method= 1
Sediment Retention Method= 0
Sediment TS Multiplier= 1
Warm Up Method= 0
XS Weighting Method= 0
Number of US Weighted Cross Sections= 1
Number of DS Weighted Cross Sections= 1
Upstream XS Weight=0
Main XS Weight=1
Downstream XS Weight=0
Number of DS XS's Weighted with US Boundary= 1
Upstream Boundary Weight= 1
Weight of XSs Associated with US Boundary= 0
Number of US XS's Weighted with DS Boundary= 1
Downstream Boundary Weight= 0.5
Weight of XSs Associated with DS Boundary= 0.5
Percentile Method= 0
Sediment Output Level= 3
Mass or Volume Output= 0
Output Increment Type= 1
Profile and TS Output Increment= 1
Transport Output Increment 1
XS Output Flag= 0
XS Output Increment= 10
Read HDF5 Sediment Hotstart= 0
Sediment Hotstart Type= 0
Write Gradation File= 0
Read Gradation Hotstart= 0
Write HDF5 File= 1
Write Binary Output= 1
Write DSS Sediment File= 0
DSS Sediment Output Type= 1
SV Curve= 0
Specific Gage Flag= 0
Subcell Erosion Methods= 0
Subcell Deposition Methods= 0
Advection Scheme= 1
Matrix Solver= 0
Implicit Weighting Factor= 1
Maximum Outer Loop Convergence Iterations= 5
Convergence Maximum Absolute= 0.001
Convergence RMSE= 0.0001
Grain Fractions Max Abs Error= 0.001
Max Subgrid Regions= 1
Max Subgrid Length Scale= 3.402823E+38
Initial Layer Thickness= 3
Min Layer Thickness= 0.1
Max Layer Thickness= 6
Number of Layers= 5

--- HckmanRn.f01 (steady flow) ---

Flow Title=Flow
Program Version=6.60
Number of Profiles= 1
Profile Names=P100yr
River Rch & RM=HckmanRn,Main,5411
     743
River Rch & RM=HckmanRn,Main,3000
     825
Boundary for River Rch & Prof#=HckmanRn,Main            , 1
Up Type= 0
Dn Type= 3
Dn Slope=0.045475
DSS Import GetInterval= 0
DSS Import GetPeak= 0
DSS Import FillOption= 0

--- HckmanRn.g01 (geometry) ---

Geom Title=Geometry
Program Version=6.60

River Reach=HckmanRn        ,Main
Reach XY= 30
     1669246.818      448372.2861668836.28886545448234.876516375
     1668678.809      448146.922      1668541.98      448209.012
     1668368.358      448204.413      1667977.42      448351.589
     1667860.132      448355.135     1667718.193      448435.153
1667554.13260265448461.510947822     1667469.201      448606.848
     1667336.972       448658.59     1667166.937      448781.115
     1667108.067      448870.157     1667007.057      448938.043
     1666942.072       449050.29     1666856.349      449106.234
     1666822.288      449336.517     1666736.384      449391.676
     1666554.328      449603.874       1666495.7      449868.194
     1666309.971      449934.638     1666217.368      450050.785
     1665789.572      450358.102     1665609.431      450380.871
     1665522.039      450442.145     1665480.892      450403.802
     1665423.669      450408.706     1665314.127      450491.271
     1665144.911      450519.065      1664925.18      450624.498

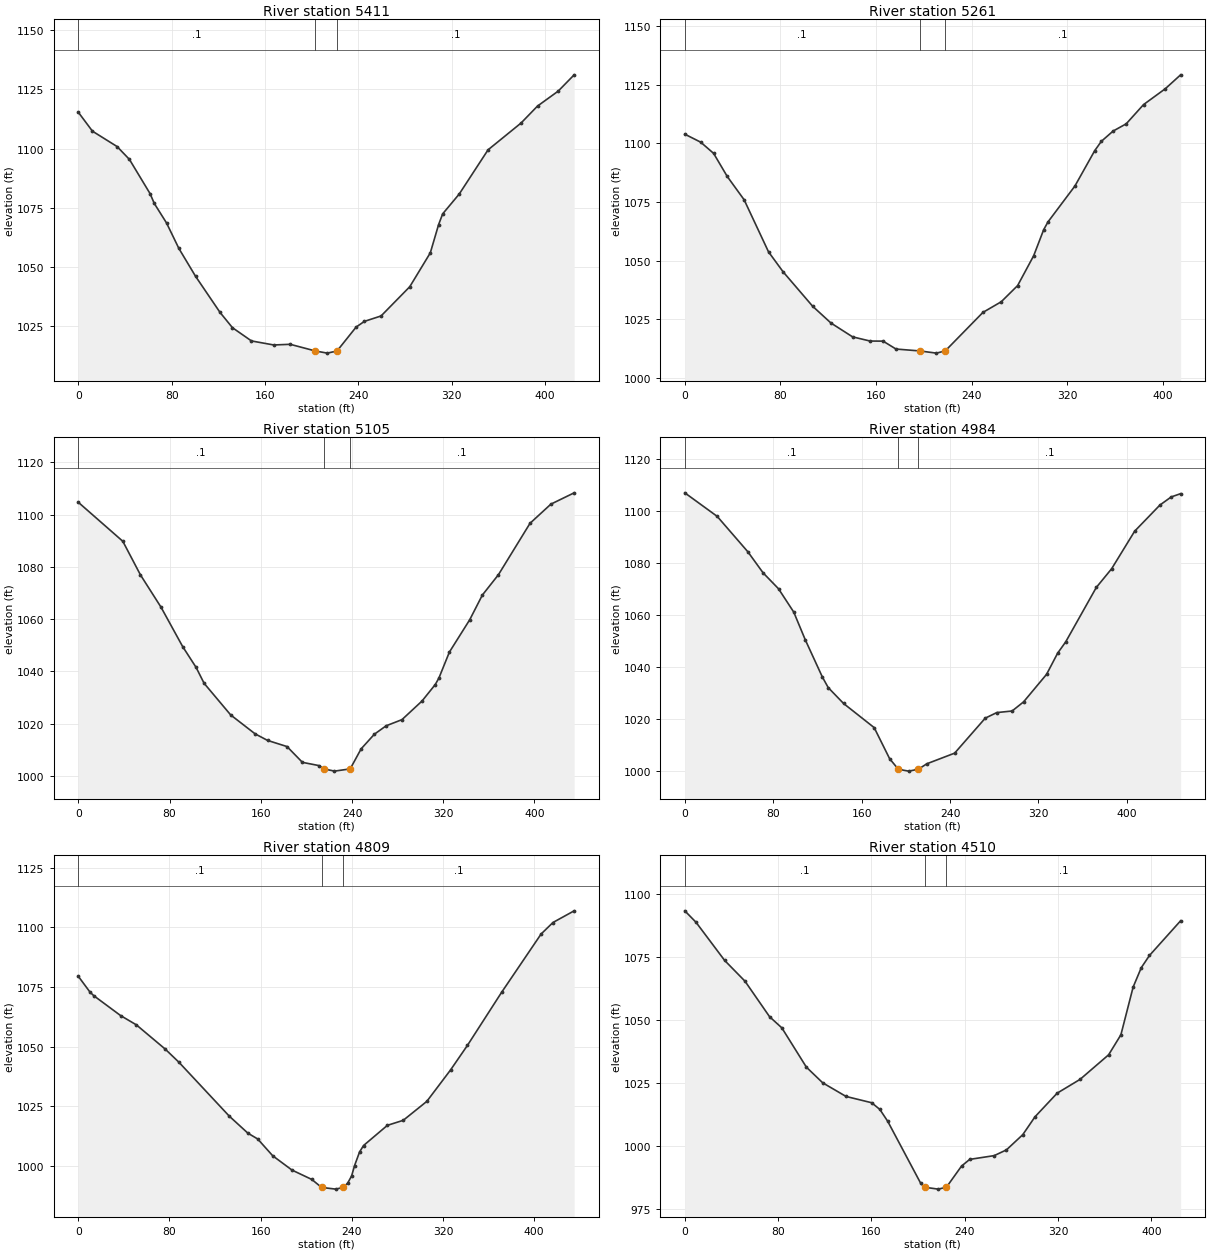
Type RM Length L Ch R = 1 ,5411    ,149.3,149.7,150.7
XS GIS Cut Line= 6
1669190.00466368 448132.878966511669157.50800951448214.120601922
1669129.65340643448283.7562894231669092.51437309448376.603872761
1669064.65977001448446.2395602611669032.16311584448527.481195673
#Sta/Elev= 30
       0 1115.31    12.1 1107.34    33.2 1100.86    43.8 1095.43    61.5 1080.99
    65.1 1076.86    75.6 1068.63    86.2 1057.87   100.5 1046.12   121.5 1030.88
   132.1 1024.47   148.4 1018.88   167.5 1017.18   181.6 1017.46   203.21014.647
   213.4 1013.74  221.741014.644   238.1 1024.72   245.2 1027.13   259.5 1029.42
   284.1 1041.75   301.7 1056.03   308.8 1067.93   312.3 1072.47   326.5 1080.84
   351.2 1099.47   379.5 1110.78   393.6 1117.93   411.3 1124.22     425  1131.1
#Mann= 3, -1 ,  0
       0     0.1       0   203.2   0.045       0  221.74     0.1       0
Bank Sta=203.2,221.74
XS Rating Curve= 0 ,0
Exp/Cntr(USF)=0,0
Exp/Cntr=0.3,0.1

Type RM Length L Ch R = 1 ,5261    ,152.8,156.7,160.2
XS GIS Cut Line= 2
1669059.92487704448089.3741678341668882.30421061448463.976995123
#Sta/Elev= 30
       0 1103.86    13.3 1100.45    24.1 1095.68    35.5 1085.84    49.6 1075.92
      70 1053.74    82.2 1045.23   106.9 1030.56   122.2 1023.42   140.3 1017.52
   154.9 1015.74   165.8  1015.7   176.6 1012.33  196.291011.532   210.4 1010.59
  217.771011.531   249.3 1027.94   264.6 1032.47   278.3 1039.36   291.7 1052.05
   300.1 1063.18   303.7 1066.49   326.2 1081.77   342.8 1096.86   348.3  1100.8
   358.1 1105.17   369.1 1108.27   383.6 1116.46   401.8 1123.22   414.6 1129.14
#Mann= 3, -1 ,  0
       0     0.1       0  196.29   0.045       0  217.77     0.1       0
Bank Sta=196.29,217.77
XS Rating Curve= 0 ,0
Exp/Cntr(USF)=0,0
Exp/Cntr=0.3,0.1

Type RM Length L Ch R = 1 ,5105    ,123.2,120.1,114.3
XS GIS Cut Line= 6
1668957.01497218448045.3725798431668908.95010768448121.902610511
1668864.29468517448184.5120653361668795.15538776448257.229439586
1668742.14433892448310.4704748391668707.80484067448395.852193832
#Sta/Elev= 30
       0 1104.67      39 1089.76    54.5 1076.88    72.5 1064.55    91.5 1049.46
   103.3 1041.48   110.3 1035.41   133.6 1023.31     155 1016.08   165.9 1013.57
     183 1011.21   196.5 1005.17   210.9 1003.94  215.371002.666   224.6 1001.81
   238.41002.665     248 1010.34   259.6 1015.93   269.9 1019.15   283.8 1021.51
   301.4 1028.64     313 1034.94   316.2 1037.43   325.4 1047.37   343.2 1059.72
   354.3 1069.18   368.4 1076.97   396.1 1096.64   414.4 1103.97   434.8  1108.3
#Mann= 3, -1 ,  0
       0     0.1       0  215.37   0.045       0   238.4     0.1       0
Bank Sta=215.37,238.4
XS Rating Curve= 0 ,0
Exp/Cntr(USF)=0,0
Exp/Cntr=0.3,0.1

Type RM Length L Ch R = 1 ,4984    ,179.2,175.9,166.4
XS GIS Cut Line= 2
1668792.39953206447971.8835687221668647.84493094448396.683174868
#Sta/Elev= 30
       0 1107.07    29.3 1098.02    57.1 1084.37    70.9 1076.26    84.8 1070.17
    98.6 1061.18     109 1050.55   124.5  1036.2   129.8 1032.13   143.7 1026.02
   171.4 1016.73   185.4 1004.75  193.331000.688   202.6    1000  211.231000.688
     219 1002.82   244.2 1006.92   271.9 1020.38   282.3 1022.52   296.2 1023.13
   306.6 1026.65   327.4 1037.25   337.4 1045.38   344.7 1049.73   372.4 1070.67
   386.3 1077.88   407.1 1092.31     430 1102.38   440.2 1105.49   448.7 1106.75
#Mann= 3, -1 ,  0
       0     0.1       0  193.33   0.045       0  211.23     0.1       0
Bank Sta=193.33,211.23
XS Rating Curve= 0 ,0
Exp/Cntr(USF)=0,0
Exp/Cntr=0.3,0.1

Type RM Length L Ch R = 1 ,4809    ,297,298.7,296.5
XS GIS Cut Line= 6
1668506.71239509447986.4885112491668529.99843776448075.825602919
1668552.13487643448152.9225615861668586.17745925448246.984053254
1668609.89427534448318.1354857531668637.56351134448401.145490333
#Sta/Elev= 30
       0 1079.45    10.2 1072.87    13.6 1071.32    37.1 1063.01    50.9 1059.13
    76.1 1049.03    88.2  1043.5   132.5 1020.86   148.8 1013.75   157.4 1011.32
   170.6 1004.27   187.5  998.29   204.9  994.36  213.44991.0264   225.9  990.31
  232.31991.0248   236.3  992.78   239.8  995.82   242.4 1000.16   246.8 1005.89
   250.3 1008.58   271.2 1017.03   285.1 1019.13   305.8 1027.07   326.6 1040.21
   341.4 1050.49   371.5  1072.8   406.1 1097.18   416.5    1102   435.1 1106.89
#Mann= 3, -1 ,  0
       0     0.1       0  213.44   0.045       0  232.31     0.1       0
Bank Sta=213.44,232.31
XS Rating Curve= 0 ,0
Exp/Cntr(USF)=0,0
Exp/Cntr=0.3,0.1

Type RM Length L Ch R = 1 ,4510    ,299.3,300,299.5
XS GIS Cut Line= 6
1668206.29337651448033.276147336 1668236.8641815448115.262203842
1668263.06786926448185.5356853461668298.00546342448279.233660668
1668324.20915118 448349.507470251668354.77962808448431.493198678
#Sta/Elev= 30
       0 1093.34     9.6 1088.81    34.1 1073.69    51.6 1065.42    72.7 1051.31
    83.2  1046.9   104.2 1031.33   118.2 1025.11   138.2  1019.7   160.2  1017.2
   167.2 1014.54   173.9 1009.87   202.2  985.25  205.52983.6795   217.2  982.93
  224.24983.6782   237.2  992.07   244.2  994.73   265.2  996.22   275.7   998.5
   289.7 1004.54   300.2 1011.64   319.2 1021.01   338.8 1026.47   363.3 1036.23
   373.8 1044.15   384.3  1063.1   391.3 1070.81   398.3 1075.63     425  1089.4
#Mann= 3, -1 ,  0
       0     0.1       0  205.52   0.045       0  224.24     0.1       0
Bank Sta=205.52,224.24
XS Rating Curve= 0 ,0
Exp/Cntr(USF)=0,0
Exp/Cntr=0.3,0.1

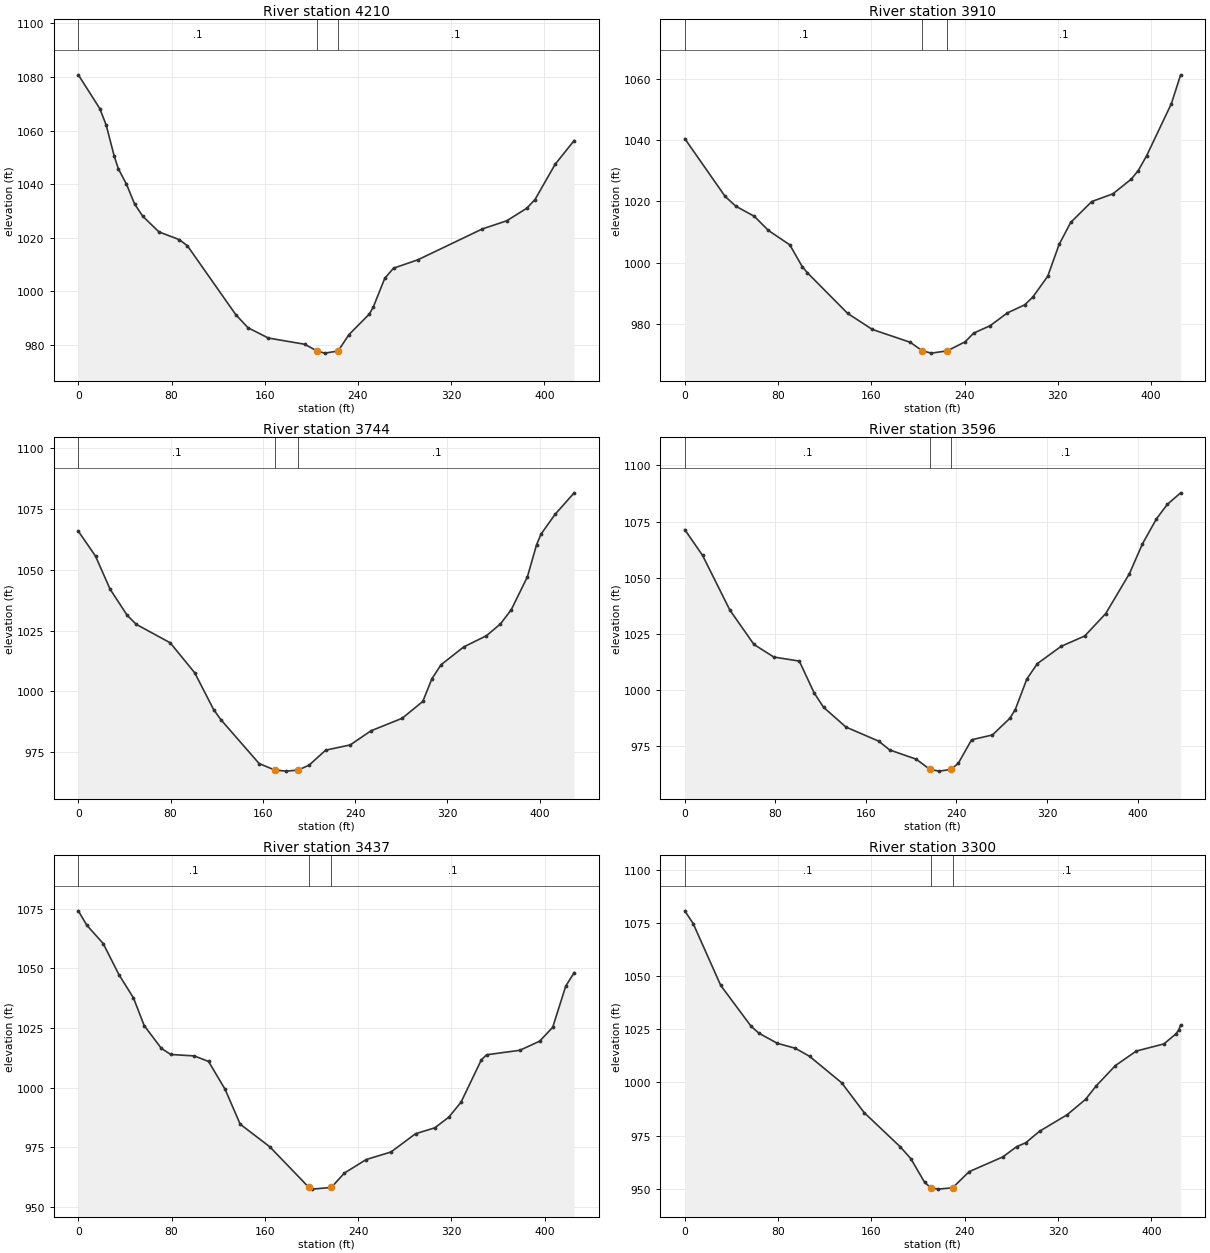
Type RM Length L Ch R = 1 ,4210    ,300.3,300,297.6
XS GIS Cut Line= 6
1667934.29293625448141.1633987581667963.95396617448224.063495427
 1667988.2780645448295.0095477551668020.71041434448389.603846759
1668045.03484076448460.5498990861668073.41339292448543.320074752
#Sta/Elev= 30
       0 1080.79    18.5 1068.12    23.9 1062.01    30.9  1050.3    34.4 1045.64
    41.3 1039.99    48.3 1032.56    55.3 1027.99    69.2 1022.14    86.6 1019.26
    93.6 1016.97   135.2   991.2   145.6  986.37     163  982.52   194.2   980.2
     205977.6667   211.5  976.88  222.87977.6679   232.3  983.82   249.7  991.46
   253.1  994.09     263 1004.84   270.5  1008.6   291.3 1011.71   346.8 1023.27
   367.6 1026.28   384.8 1030.97   391.9 1034.23   409.2  1047.4   425.5 1056.26
#Mann= 3, -1 ,  0
       0     0.1       0     205   0.045       0  222.87     0.1       0
Bank Sta=205,222.87
XS Rating Curve= 0 ,0
Exp/Cntr(USF)=0,0
Exp/Cntr=0.3,0.1

Type RM Length L Ch R = 1 ,3910    ,167.3,165.6,164.5
XS GIS Cut Line= 6
1667647.55335225448233.6162978411667678.58937943448315.692249179
1667706.76911309448385.3066112551667749.06364793448475.921915591
1667780.78471309448543.8837219181667817.79284118448623.172277257
#Sta/Elev= 30
       0 1040.42    34.6  1021.6    43.8 1018.41    59.6 1015.14    71.7 1010.53
    90.1 1005.82   100.7  998.76   105.2  996.72   139.7   983.5   160.9  978.27
   193.4  974.09  203.75971.3078   211.5  970.56   225.2971.3082   240.5  974.26
   247.8  977.09   261.9  979.49   276.7  983.66   291.5  986.28   298.4  988.76
   311.3   995.6   321.1 1005.98     331 1013.13   349.1 1019.94   367.2 1022.45
   382.9 1027.22     389 1030.04   396.2  1034.9   417.4 1051.85   425.3 1061.21
#Mann= 3, -1 ,  0
       0     0.1       0  203.75   0.045       0   225.2     0.1       0
Bank Sta=203.75,225.2
XS Rating Curve= 0 ,0
Exp/Cntr(USF)=0,0
Exp/Cntr=0.3,0.1

Type RM Length L Ch R = 1 ,3744    ,150.4,148.5,144.2
XS GIS Cut Line= 2
1667466.67591727  448305.52420821667704.90647934448663.290953363
#Sta/Elev= 30
       0 1065.82    14.9 1055.58    27.5 1042.03    42.4 1031.22    50.3 1027.53
    79.6 1019.98   100.9 1007.64   117.3  992.51   123.5  988.42   156.7  970.36
  170.26967.6893   180.4  967.24   190.8  967.69   200.2  969.77   214.4  975.85
   235.7  978.01   253.7  983.81   280.7  988.95   298.6  995.88   306.5  1005.2
   314.4 1010.95   334.1 1018.27   353.8 1022.88   365.9 1027.71   375.3 1033.58
   389.3 1047.12   397.2 1060.22   401.1 1064.64   413.2  1072.7   429.8 1081.58
#Mann= 3, -1 ,  0
       0     0.1       0  170.26   0.045       0   190.8     0.1       0
Bank Sta=170.26,190.8
XS Rating Curve= 0 ,0
Exp/Cntr(USF)=0,0
Exp/Cntr=0.3,0.1

Type RM Length L Ch R = 1 ,3596    ,156.2,158.9,161.3
XS GIS Cut Line= 6
1667326.19605534448431.9338145851667394.79073443448495.319514588
1667454.90478742448548.6930955051667534.84130734448611.867509842
 1667589.5583895448663.1151107551667653.39061092448722.900096178
#Sta/Elev= 30
       0  1071.4    15.7 1059.93    39.8  1035.6    61.1 1020.27    78.7 1014.66
   101.2 1012.85   114.3  998.68   122.6  992.28   142.4  983.47   171.4  977.18
     181  973.28   204.4  969.18  216.62964.6025   224.8  963.84  235.42964.6041
   241.7  967.38   253.4  977.81   271.8  979.95   287.2  987.37     292  991.26
   302.3 1004.95   311.6 1011.77   332.5 1019.42   353.4 1024.05   371.9 1034.02
   392.8 1051.75   404.4  1065.1   416.7 1076.19   426.3 1082.64   438.1 1087.81
#Mann= 3, -1 ,  0
       0     0.1       0  216.62   0.045       0  235.42     0.1       0
Bank Sta=216.62,235.42
XS Rating Curve= 0 ,0
Exp/Cntr(USF)=0,0
Exp/Cntr=0.3,0.1

Type RM Length L Ch R = 1 ,3437    ,137,136.9,137.6
XS GIS Cut Line= 2
1667235.17978805448483.1448746221667483.51199939448828.284558192
#Sta/Elev= 30
       0 1074.03     7.2 1068.05    21.3 1060.35    34.9 1047.25    47.3 1037.55
    56.5 1025.98    71.2 1016.46    79.3 1013.89    99.5 1013.29   111.7 1010.96
   125.9  999.28   138.8  984.72   164.2  975.25  197.76958.2351   200.6  957.53
  216.96958.2339   228.1  964.24   246.9  969.92   268.1  973.07   289.2  980.73
   305.7  983.19   317.8   987.7   328.2  993.95   345.6 1011.65   350.1 1013.77
   378.6 1015.65   395.6 1019.46   406.8 1025.28     418 1042.53   425.2 1048.16
#Mann= 3, -1 ,  0
       0     0.1       0  197.76   0.045       0  216.96     0.1       0
Bank Sta=197.76,216.96
XS Rating Curve= 0 ,0
Exp/Cntr(USF)=0,0
Exp/Cntr=0.3,0.1

Type RM Length L Ch R = 1 ,3300    ,300.5,300.4,296.2
XS GIS Cut Line= 6
  1667125.199082448550.5546403381667173.80692442448623.311384588
1667215.47088309448685.6741207541667271.02260926448768.824545011
1667312.68656792448831.1872811761667361.29408225448903.944025427
#Sta/Elev= 30
       0 1080.73     7.2  1074.7    30.8 1045.63    56.8 1026.43    63.5 1023.17
    79.2 1018.42    94.7 1016.06   106.9 1012.29   134.5  999.79   153.8  985.75
   184.6  969.73   193.7  964.14   205.5  953.03  210.84 950.402   217.3  949.77
  229.55950.4017   243.7  957.98   272.6  964.93   284.4  969.73   292.3  971.61
   304.1  977.02   327.8   984.8   343.6  992.07   352.5  998.28   369.1 1007.92
     387 1014.74   410.7 1018.11   421.1  1022.9   423.5  1024.8     425 1027.07
#Mann= 3, -1 ,  0
       0     0.1       0  210.84   0.045       0  229.55     0.1       0
Bank Sta=210.84,229.55
XS Rating Curve= 0 ,0
Exp/Cntr(USF)=0,0
Exp/Cntr=0.3,0.1

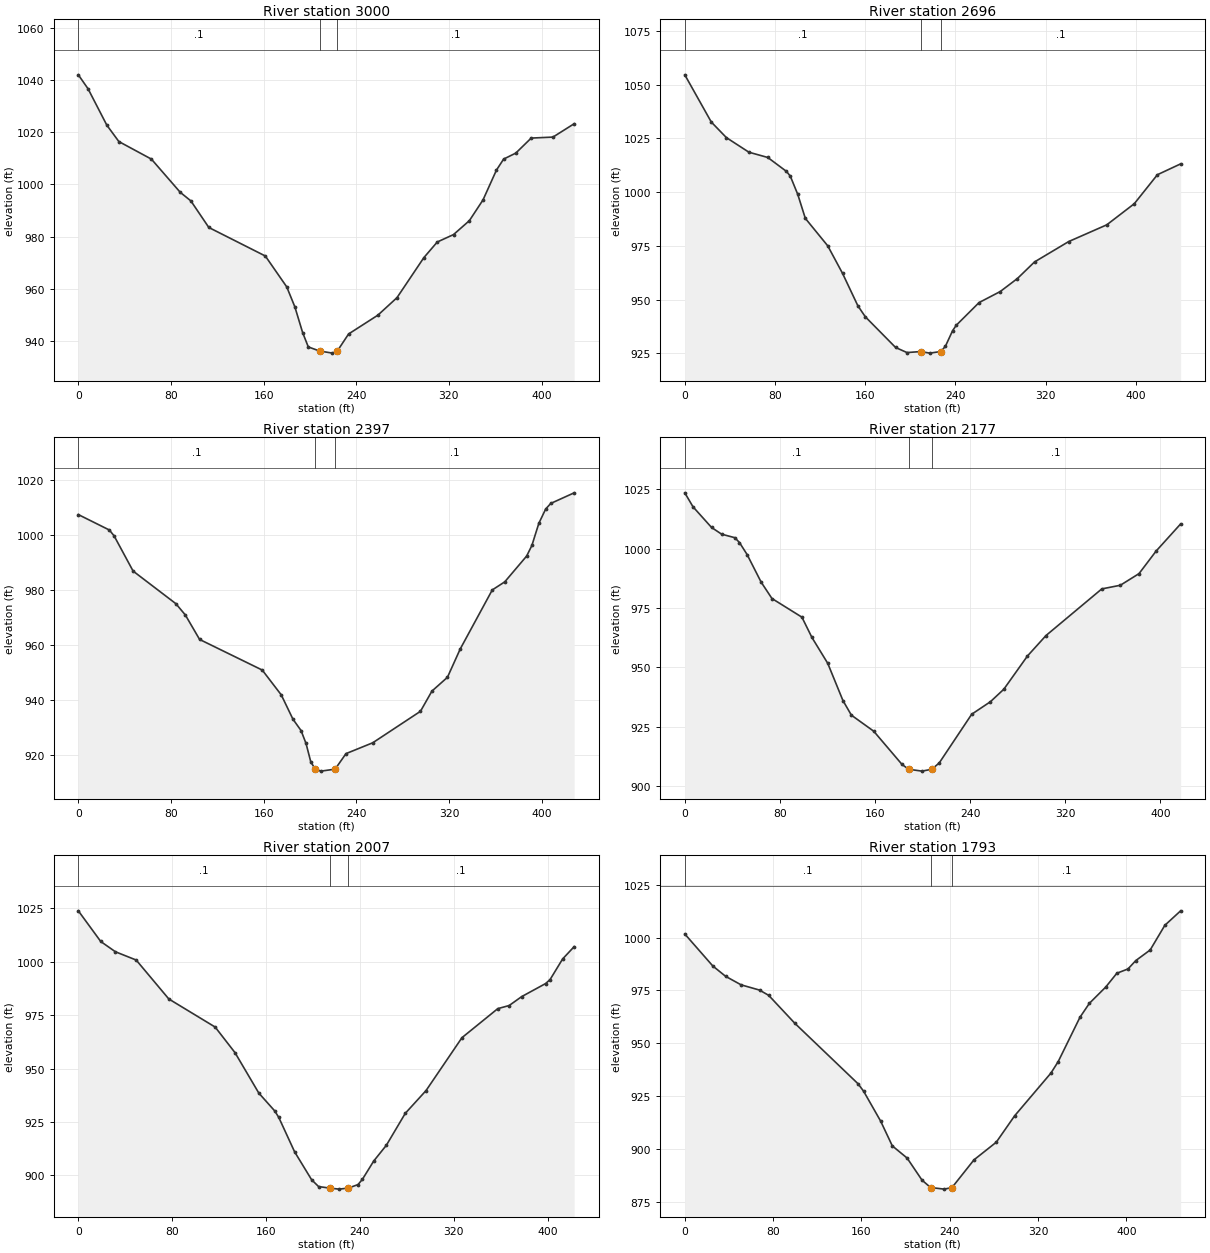
Type RM Length L Ch R = 1 ,3000    ,305.1,303.4,294.2
XS GIS Cut Line= 6
1666872.02668808448772.3137112561666934.36186525448833.718444094
1666987.79220459 448886.350884751667058.50072458448957.068263009
1667108.60462701449013.8243830951667169.53068626449080.091310918
#Sta/Elev= 30
       0  1041.9     8.4 1036.55    24.6 1022.64      35 1016.36    63.1 1009.64
      88  996.94    97.2  993.64   112.7  983.47   161.5  972.55     180  960.72
     187  953.08   193.7  943.26   198.6  937.75  208.37936.1896   219.5  935.38
  223.67936.1882   233.4  942.71   258.7  949.91   275.2  956.61   298.4  971.93
     310  977.92     324  980.75   337.7  986.08   349.5  994.03   361.1 1005.44
   367.3 1009.65   377.8 1011.94   391.1 1017.69   409.9 1018.07   428.2 1023.18
#Mann= 3, -1 ,  0
       0     0.1       0  208.37   0.045       0  223.67     0.1       0
Bank Sta=208.37,223.67
XS Rating Curve= 0 ,0
Exp/Cntr(USF)=0,0
Exp/Cntr=0.3,0.1

Type RM Length L Ch R = 1 ,2696    ,294.8,299.3,302.2
XS GIS Cut Line= 6
1666626.16169426449107.1398132591666712.26093151449122.925542846
1666786.16465509449135.6765015871666884.00238593449157.730591342
1666953.85132758449198.4978982511667038.11034542449244.681860998
#Sta/Elev= 30
       0 1054.52    23.5 1032.56    36.9 1025.31    56.9 1018.52    73.6 1016.08
    90.2 1009.59    93.6 1007.38   100.2  998.91   106.9  987.76   126.8  974.97
   139.9  962.19   153.5   947.1   160.1  941.99     187  927.69   197.1  925.33
   209.2   925.8   217.3  925.07  227.19925.8248   231.2   928.3   237.5  935.47
   240.8  938.04     261  948.58   279.8  953.72     295  959.76   310.2  967.48
   340.5  976.96   374.3  984.75   398.7  994.57   419.2 1008.05   439.8  1013.1
#Mann= 3, -1 ,  0
       0     0.1       0   209.2   0.045       0  227.19     0.1       0
Bank Sta=209.2,227.19
XS Rating Curve= 0 ,0
Exp/Cntr(USF)=0,0
Exp/Cntr=0.3,0.1

Type RM Length L Ch R = 1 ,2397    ,220.7,219.5,218.1
XS GIS Cut Line= 6
1666565.55715667449265.2789326761666635.55340776449317.784077004
1666695.55328776449362.784315094 1666771.7765605 449427.81994617
1666822.79220651449484.5035598431666878.19203009449554.286228672
#Sta/Elev= 30
       0 1007.55    26.8 1001.93    30.9  999.79    47.3  986.98    84.2  975.12
    92.4     971   104.7   962.1   158.8  950.95   175.2  941.92   185.3  933.07
   192.3  928.93   196.6  924.22   200.7  917.55  204.53914.8789   209.5  914.16
   221.7  914.88   231.1  920.53   254.2  924.48   295.4  935.94   305.3  943.29
   318.7  948.32   329.7   958.6   357.4  980.12   368.2  983.07   387.1  992.46
   391.6  996.31   397.6 1004.36   403.5 1009.57   407.9 1011.61   428.1 1015.47
#Mann= 3, -1 ,  0
       0     0.1       0  204.53   0.045       0   221.7     0.1       0
Bank Sta=204.53,221.7
XS Rating Curve= 0 ,0
Exp/Cntr(USF)=0,0
Exp/Cntr=0.3,0.1

Type RM Length L Ch R = 1 ,2177    ,173.8,170.7,168
XS GIS Cut Line= 2
 1666423.6806296449452.0614009351666773.87113781449678.506705521
#Sta/Elev= 30
       0 1023.53     6.9 1017.64    22.5 1008.93      31 1006.09    42.1 1004.61
      46 1002.56    52.4  997.51    64.2  985.88    73.3  978.97    98.5   971.1
   106.9  962.56   120.2  951.66     133  935.95   140.1  929.79   158.9  923.02
   182.7     909  188.24906.9804   199.5  906.19  207.77906.9803     214  909.65
   241.3  930.18     257  935.44   268.3  940.72   288.2  954.74   303.8  963.37
   350.7  983.02   366.3  984.56     382  989.46   396.4  998.98     417 1010.41
#Mann= 3, -1 ,  0
       0     0.1       0  188.24   0.045       0  207.77     0.1       0
Bank Sta=188.24,207.77
XS Rating Curve= 0 ,0
Exp/Cntr(USF)=0,0
Exp/Cntr=0.3,0.1

Type RM Length L Ch R = 1 ,2007    ,198.3,213.8,219.7
XS GIS Cut Line= 3
1666356.83902535449590.6003146571666476.95250001449699.544783386
1666728.61436552 449766.30762791
#Sta/Elev= 30
       0 1023.85    19.1  1009.5    31.6 1004.69    49.3 1000.82    77.1   982.6
   116.6  969.45   133.5  957.48   153.8  938.55   167.4  930.18   170.8  927.17
   184.3  911.06   198.8  897.99   204.7  894.82   214.2  894.09   222.2  893.61
229.9993  894.09   238.3  895.73     242  898.14   251.7  906.75   262.5  914.16
   278.6  929.08   296.3  939.74   326.9  964.49   357.4  978.07   367.1  979.53
   377.8  983.71   398.2  989.82     402   991.7   412.7 1001.35   422.5 1007.09
#Mann= 3, -1 ,  0
       0     0.1       0   214.2   0.045       0229.9993     0.1       0
Bank Sta=214.2,229.9993
XS Rating Curve= 0 ,0
Exp/Cntr(USF)=0,0
Exp/Cntr=0.3,0.1

Type RM Length L Ch R = 1 ,1793    ,297.1,291.7,286.8
XS GIS Cut Line= 6
1666313.03764859449704.0982650071666382.38002959 449774.33532925
1666437.83759584449840.8493038421666460.31753775449939.221810505
1666466.44515017450013.9710048441666483.93166375450100.194585666
#Sta/Elev= 30
       0 1001.76    25.4  986.59      37   981.7      51  977.68    67.7  975.19
      76   972.7    99.7  959.46   156.9  930.85     162  927.29   177.4  913.16
     188   901.4   201.4  895.64   214.9  885.19  222.68 881.674   235.1  880.92
  242.08 881.675     262  894.79   282.2  903.15   298.8  915.63   331.7  935.88
   338.3  941.33     358  962.31   366.6  968.96   381.4  976.65   391.4  983.16
   401.5   985.2   408.6  989.17   421.6  994.18   434.9 1005.87   449.2 1012.73
#Mann= 3, -1 ,  0
       0     0.1       0  222.68   0.045       0  242.08     0.1       0
Bank Sta=222.68,242.08
XS Rating Curve= 0 ,0
Exp/Cntr(USF)=0,0
Exp/Cntr=0.3,0.1

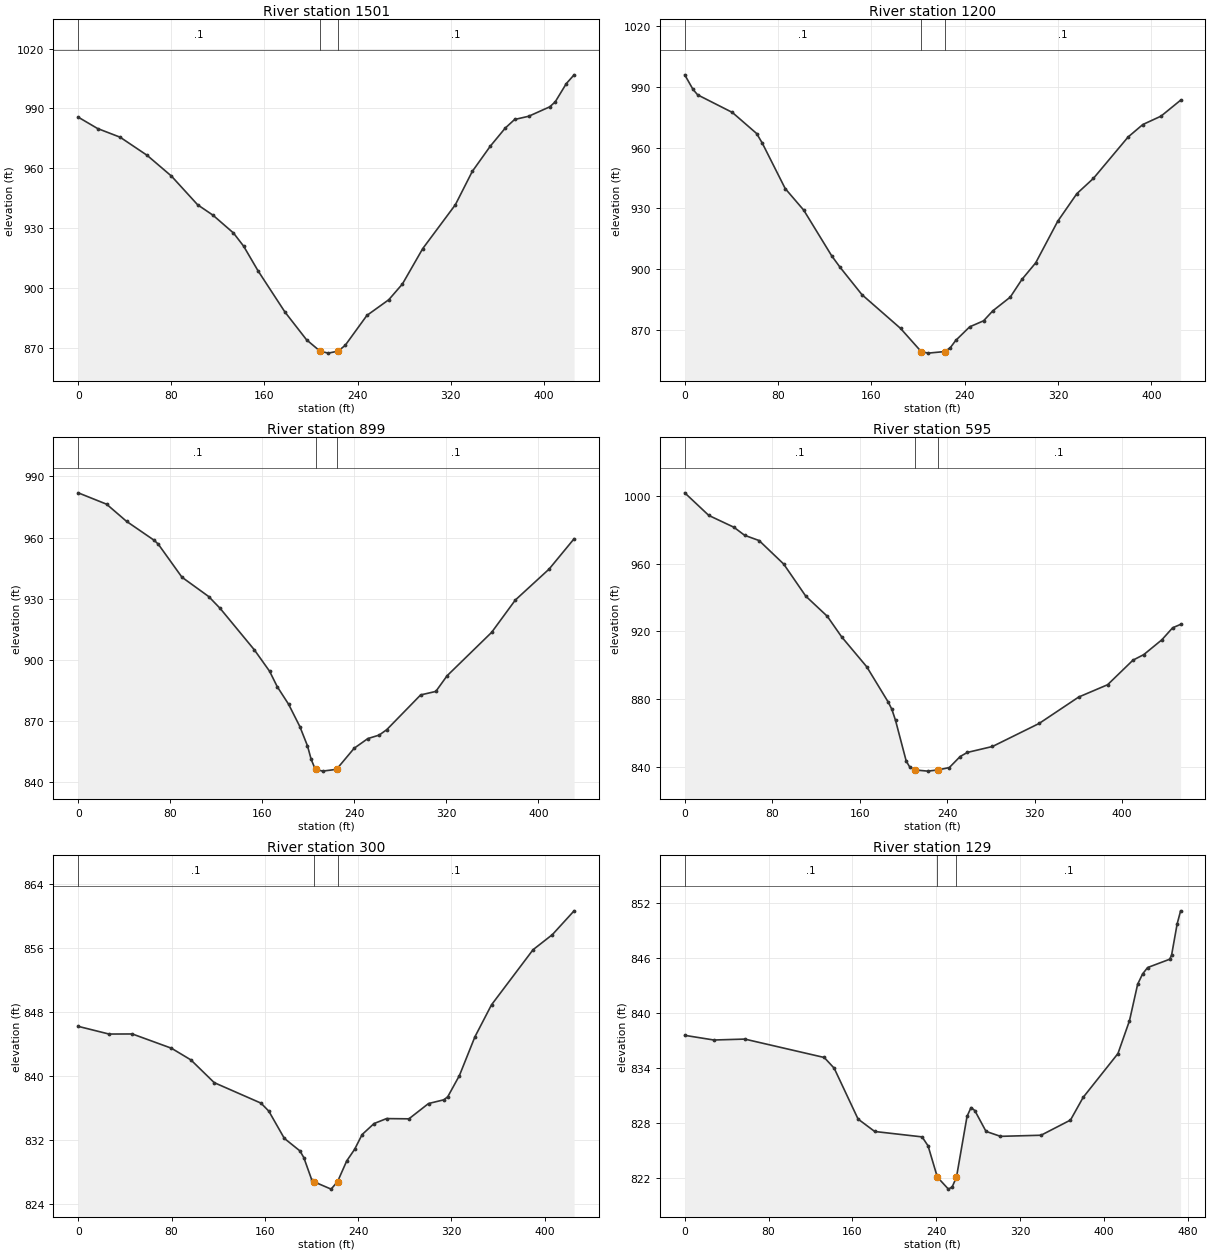
Type RM Length L Ch R = 1 ,1501    ,300,301.1,302.9
XS GIS Cut Line= 6
1666077.00104718  449889.21797351666136.78603259449954.104982838
1666186.83153617450010.3246866761666257.88191901450080.727433011
1666312.29158708450132.347408503 1666375.7694785450192.570057094
#Sta/Elev= 30
       0  985.59    16.6   979.9      36  975.54    59.2  966.45    80.1  956.04
   102.6  941.65   115.8  936.43   133.4   927.5   142.1  920.92   154.4  908.63
   177.6  887.89   196.2  873.94  207.75868.2756   214.8  867.28   223.3868.2735
   229.4  871.21     248  886.18   266.8  894.05   278.5  901.92     296  919.71
     324  941.67   338.5  958.35     354  971.03   366.9  980.14   374.9  984.42
     387  986.04   405.1  990.77   409.8  993.27   419.3  1002.4     426 1006.81
#Mann= 3, -1 ,  0
       0     0.1       0  207.75   0.045       0   223.3     0.1       0
Bank Sta=207.75,223.3
XS Rating Curve= 0 ,0
Exp/Cntr(USF)=0,0
Exp/Cntr=0.3,0.1

Type RM Length L Ch R = 1 ,1200    ,294.8,301,305.7
XS GIS Cut Line= 6
1665850.55661817450031.1215610951665899.33243926450103.765444666
1665941.14009842450166.032052428 1665996.8847376450249.053539917
1666039.61398284450310.7010544241666090.14078468450382.169743508
#Sta/Elev= 30
       0  995.91     7.1   988.7    11.1  986.01    40.8  977.34    61.6  966.94
    66.4  962.26    86.1  939.76     102  929.08   125.9  906.59     133  900.98
   151.9  887.36     185  870.69  202.65859.2712   208.6   858.5  222.71859.2693
   227.6  861.18   232.2  864.74   244.2  871.48   256.1  874.45     264  879.36
     279  886.16     289  894.91   300.8  903.08   319.6  923.54   336.1  937.26
   350.3   944.8     380  965.22   392.6  971.37   408.2  975.51     425  983.39
#Mann= 3, -1 ,  0
       0     0.1       0  202.65   0.045       0  222.71     0.1       0
Bank Sta=202.65,222.71
XS Rating Curve= 0 ,0
Exp/Cntr(USF)=0,0
Exp/Cntr=0.3,0.1

Type RM Length L Ch R = 1 ,899     ,303.9,303.6,301.7
XS GIS Cut Line= 6
1665689.84663776 450151.274207921665717.54572934450237.018130928
 1665728.0663776450312.0156843361665724.44040059450411.968240336
1665722.60018118450487.9949911681665726.64774525450577.069616169
#Sta/Elev= 30
       0  981.96    24.7  976.38      42  967.98    66.1  958.65    69.6  956.78
    90.2  940.56   113.4   931.1   123.4  925.27   153.2  904.88   166.4  894.42
     173  886.89   182.9  878.25   192.7  867.28   199.3  857.86   202.5  851.26
   205.8  846.75  207.11 846.317   212.4  845.44  224.56846.3164   239.9  856.66
   251.8  861.41   261.6  863.11   268.2  865.76   297.7  882.82   310.9  884.54
   320.7  892.23   359.4   913.5     380  929.36   409.4  944.57   431.1  959.43
#Mann= 3, -1 ,  0
       0     0.1       0  207.11   0.045       0  224.56     0.1       0
Bank Sta=207.11,224.56
XS Rating Curve= 0 ,0
Exp/Cntr(USF)=0,0
Exp/Cntr=0.3,0.1

Type RM Length L Ch R = 1 ,595     ,293.1,295.5,287.4
XS GIS Cut Line= 6
1665456.72997801450192.2275380941665460.99309283450279.623688757
1665464.64695692450354.534300089 1665460.1299056450462.284084588
1665465.98192801450548.9892917571665477.63807267450644.599664837
#Sta/Elev= 30
       0 1002.07      22  988.69      45  981.68    54.8  976.91      68  973.82
    90.5  959.91   110.7   940.9   130.4  928.96   143.5   916.8   166.5  899.04
   186.2  878.08   189.5  873.81   192.8  867.34   202.6  843.19   205.9   839.6
   210.8837.9479   222.3  837.26  231.36 837.948     242  839.36   251.9  845.89
   258.5  848.33   281.5  851.85   324.2   865.5   360.4  881.15   386.8  888.42
     410  902.97   419.9  906.26   436.4  915.01   446.3  922.15   453.6  924.17
#Mann= 3, -1 ,  0
       0     0.1       0   210.8   0.045       0  231.36     0.1       0
Bank Sta=210.8,231.36
XS Rating Curve= 0 ,0
Exp/Cntr(USF)=0,0
Exp/Cntr=0.3,0.1

Type RM Length L Ch R = 1 ,300     ,173.5,171.2,168.9
XS GIS Cut Line= 6
1665159.98418042450299.8014699221665176.46479051450385.735353172
1665190.59074651450459.3933423461665209.42535451 450557.60344775
 1665221.8938335450631.5790215881665235.57228383450718.050305337
#Sta/Elev= 30
       0  846.22    26.4  845.26    46.4  845.27    79.9  843.49    96.6  842.03
   116.6  839.19   156.7  836.63   163.4  835.63   176.7  832.23   190.1  830.66
   193.4  829.83   200.1  827.09  201.77826.8297   216.8  825.89  222.35826.8303
   230.2  829.42   236.9  830.85   243.4  832.71   253.6  834.08   264.3   834.7
   283.5  834.67   300.3  836.58   313.5  837.05   316.8  837.43   326.8  840.08
   340.1  844.92   354.3  848.91   389.9  855.79   406.5  857.68   425.1  860.65
#Mann= 3, -1 ,  0
       0     0.1       0  201.77   0.045       0  222.35     0.1       0
Bank Sta=201.77,222.35
XS Rating Curve= 0 ,0
Exp/Cntr(USF)=0,0
Exp/Cntr=0.3,0.1

Type RM Length L Ch R = 1 ,129     ,,,
XS GIS Cut Line= 4
1665094.29216908450330.2411735291665027.57396527450538.094039274
1665069.91436384450633.0391754781665193.08643243450720.286057396
#Sta/Elev= 30
       0  837.58    27.8  837.07    57.3  837.17   133.1  835.16   142.6  833.99
   165.4  828.43   181.3  827.07   226.5  826.48   232.2   825.5  241.05822.0858
   251.6  820.77   255.2  821.01  259.32822.0874   269.4  828.73   273.2  829.69
   276.8  829.36   287.5  827.08   301.3  826.54     340  826.66   368.1  828.32
   380.2   830.8   413.4  835.59   424.4  839.18   432.2  843.17   436.9  844.29
   441.7  844.99   462.8   845.9   464.6  846.36   469.9  849.77   473.2  851.19
#Mann= 3, -1 ,  0
       0     0.1       0  241.05   0.045       0  259.32     0.1       0
Bank Sta=241.05,259.32
XS Rating Curve= 0 ,0
Exp/Cntr(USF)=0,0
Exp/Cntr=0.3,0.1
LCMann Table=0

Chan Stop Cuts=-1
Use User Specified Reach Order=0
Composite Channel Slope=5